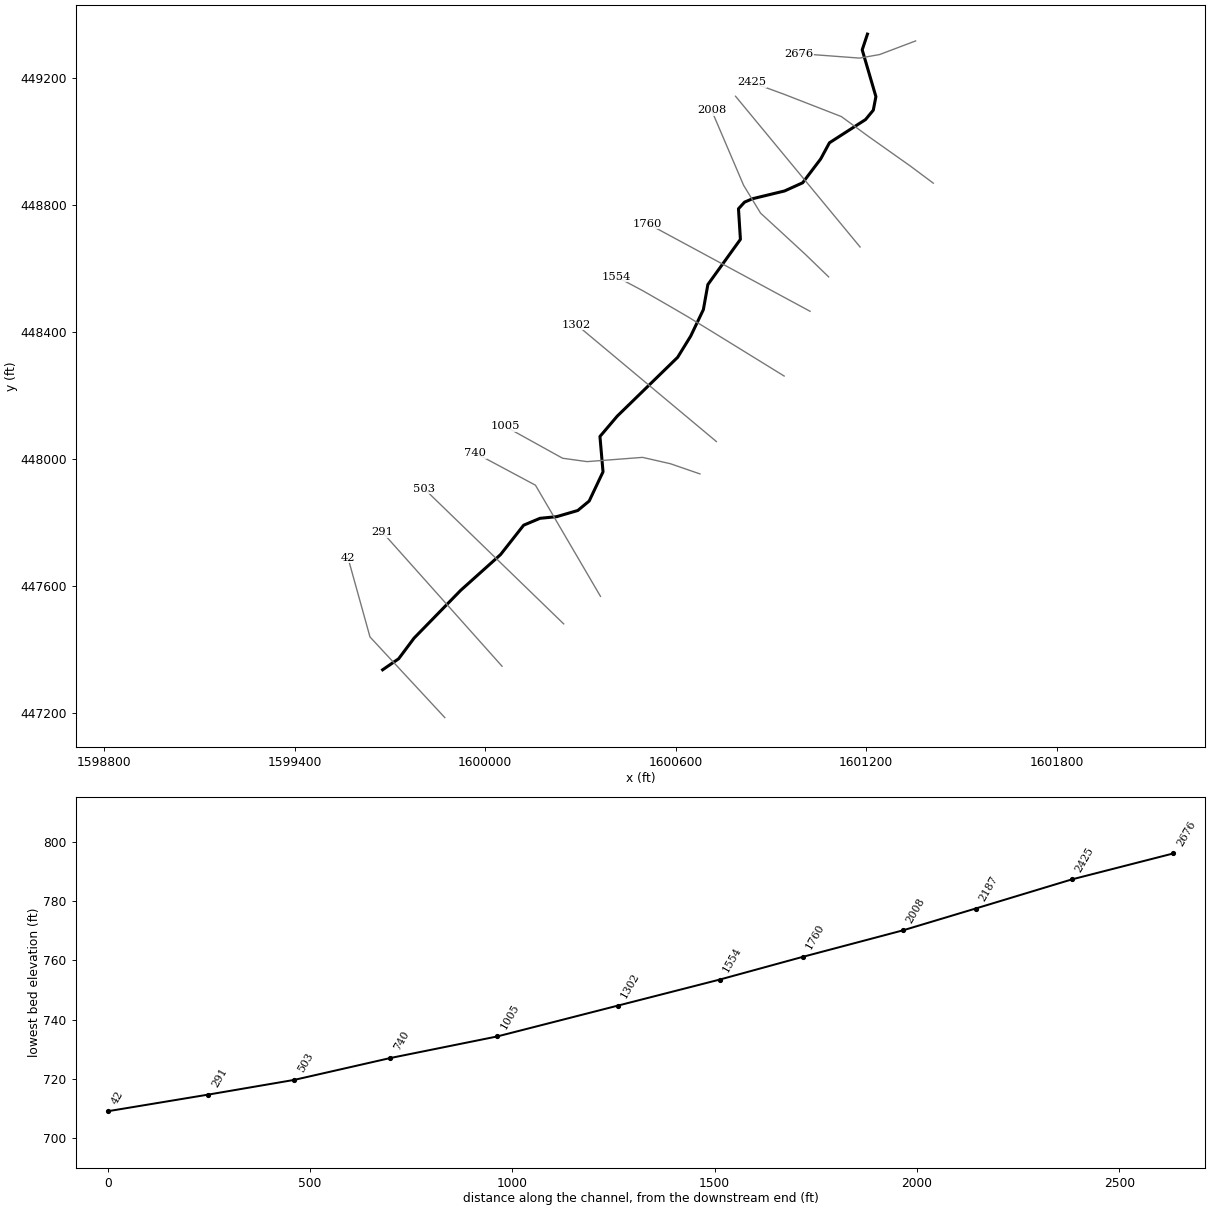
--- DryRn.prj (project) ---

Proj Title=DryRn
Current Plan=p01
Default Exp/Contr=0,0
English Units
Geom File=g01
Flow File=f01
Plan File=p01
BEGIN DESCRIPTION:
---------- MODELED AS PART OF WVEM CTP PROGRAM, 2025----------
Stream Name: Dry Run
Flood Zone: AFH
Marshall County, WV
HEC-RAS Version: RAS 6.6
Vertical Datum: NAVD88
Projection: NAD 1983 StatePlane West Virginia N FIPS 4701 (US Feet)
Terrain: 1-meter West Virginia FEMA R3 South Central (collected 2018-2019)
Land Use: 2024 NLCD
Hydrologic Method:
Duda et al., "Estimation of magnitude and frequency of floods for rural, unregulated streams in and near Virginia and West Virginia." September 8, 2025.
Additional Model Notes:
None
END DESCRIPTION:
DSS Export Rating Curves= 0
DSS Export Rating Curve Sorted= 0
DSS Export Volume Flow Curves= 0
DXF OffsetX= 0
DXF OffsetY= 0
DXF ScaleX= 0
DXF ScaleY= 0

--- DryRn.p01 (plan) ---

Plan Title=Floodplain
Program Version=6.60
Short Identifier=Floodplain
Geom File=g01
Flow File=f01
Subcritical Flow
K Sum by GR= 0
Std Step Tol= 0.01
Critical Tol= 0.01
Num of Std Step Trials= 20
Max Error Tol= 0.3
Flow Tol Ratio= 0.001
Split Flow NTrial= 30
Split Flow Tol= 0.02
Split Flow Ratio= 0.02
Log Output Level= 0
Friction Slope Method= 1
Unsteady Friction Slope Method= 2
Unsteady Bridges Friction Slope Method= 1
Parabolic Critical Depth
Global Vel Dist= 0 , 0 , 0
Global Log Level= 0
CheckData=False
Encroach Param=-1 ,0,0, 0
Flow Ratio Tolerance=0.1
Flow Ratio Min Ratio=0.5
Flow Ratio Max Ratio=4
Flow Ratio Max Iterations= 10
Mapping Interval=1HOUR
Computation Time Step Use Courant=        0
Computation Time Step Use Time Series=    0
Computation Time Step Count To Double=0
Computation Time Step Max Doubling=0
Computation Time Step Max Halving=0
Computation Time Step Residence Courant=0
Run HTab= 0
Run UNet= 0
Run Sediment= 0
Run PostProcess= 0
Run WQNet= 0
Run RASMapper=-1
UNET Theta= 0
UNET Theta Warmup= 0
UNET ZTol= 0
UNET ZSATol= 0
UNET MxIter= 0
UNET Max Iter WO Improvement= 0
UNET MaxInSteps= 0
UNET DtIC= 0
UNET DtMin= 0
UNET MaxCRTS= 0
UNET WFStab= 0
UNET SFStab= 0
UNET WFX= 1
UNET SFX= 1
UNET Gravity=32.17405
UNET 1D Methodology=Finite Difference
UNET DSS MLevel= 1
UNET Pardiso=0
UNET DZMax Abort= 0
UNET Use Existing IB Tables= 0
UNET Froude Reduction=False
UNET Froude Limit= 0
UNET Froude Power= 0
UNET D1 Cores= 0
UNET WindReference=Eulerian
UNET WindDragFormulation=Hsu (1988)
UNET D2 Coriolis=0
UNET D2 Cores= 0
UNET D2 Theta= 1
UNET D2 Theta Warmup= 1
UNET D2 Z Tol= 0.01
UNET D2 Volume Tol= 0.01
UNET D2 Max Iterations= 20
UNET D2 Advanced Convergence=0
UNET D2 WS Max Tol=0.15
UNET D2 WS RMS Tol=0.002
UNET D2 WS Stall Tol=1
UNET D2 Equation= 0
UNET D2 RampUpFraction=0.1
UNET D2 TimeSlices= 1
UNET D2 Turbulence Formulation=Non-Conservative (original)
UNET D2 Eddy Viscosity=0.3
UNET D2 Transverse Eddy Viscosity=0.1
UNET D2 Smagorinsky Mixing=0
UNET D2 BCVolumeCheck=0
UNET D2 Cores=0
UNET D2 SolverType=PARDISO (Direct)
UNET D2 Minimum Iterations= 3
UNET D2 Maximum Iterations= 30
UNET D2 Restart Number= 10
UNET D2 Relaxation Coeff=1.3
UNET D2 SOR Precondition Iterations= 10
UNET D2 ILUT Maximum Fill= 8
UNET D2 ILUT Tolerance=1E-08
UNET D2 Convergence Tolerance=0.00001
PS Theta= 1
PS WS Tol= 0.01
PS Volume Tol= 0.01
PS Max Iterations= 20
PS Equation= 0
PS Advance Time Step=-1
PS Target Courant=0.9
PS Time Slices= 1
PS Iterate With 2D=0
PS Project Initial WSE from DS=-1
PS Ramp Up Initial WSE from US=-1
PS Cores=0
UNET D1D2 MaxIter= 0
UNET D1D2 ZTol=0.01
UNET D1D2 QTol=0.1
UNET D1D2 MinQTol=1
Write IC File= 0
Write IC File at Fixed DateTime=0
Write IC File at Sim End=0
Echo Input=False
Echo Parameters=False
Echo Output=False
Write Detailed= 0
HDF Write Warmup=0
HDF Write Time Slices=0
HDF Flush=0
HDF Compression= 1
HDF Chunk Size= 1
HDF Spatial Parts= 1
HDF Use Max Rows=0
HDF Fixed Rows= 1
Calibration Method= 0
Calibration Iterations= 20
Calibration Max Change=0.05
Calibration Tolerance=0.2
Calibration Maximum=1.5
Calibration Minimum=0.5
Calibration Optimization Method= 1
WQ AD Non Conservative
WQ ULTIMATE=-1
WQ Max Comp Step=1HOUR
WQ Output Interval=15MIN
WQ Output Selected Increments= 0
WQ Create Restart=0
WQ Fixed Restart=0
WQ System Summary=0
WQ Write To DSS=0
Sorting and Armoring Iterations= 10
XS Update Threshold= 0.02
Bed Roughness Predictor= 0
Processes Affected by Predictor=Sediment Only
Hydraulics Update Threshold= 0.02
Energy Slope Method= 1
Volume Change Method= 1
Sediment Retention Method= 0
Sediment TS Multiplier= 1
Warm Up Method= 0
XS Weighting Method= 0
Number of US Weighted Cross Sections= 1
Number of DS Weighted Cross Sections= 1
Upstream XS Weight=0
Main XS Weight=1
Downstream XS Weight=0
Number of DS XS's Weighted with US Boundary= 1
Upstream Boundary Weight= 1
Weight of XSs Associated with US Boundary= 0
Number of US XS's Weighted with DS Boundary= 1
Downstream Boundary Weight= 0.5
Weight of XSs Associated with DS Boundary= 0.5
Percentile Method= 0
Sediment Output Level= 3
Mass or Volume Output= 0
Output Increment Type= 1
Profile and TS Output Increment= 1
Transport Output Increment 1
XS Output Flag= 0
XS Output Increment= 10
Read HDF5 Sediment Hotstart= 0
Sediment Hotstart Type= 0
Write Gradation File= 0
Read Gradation Hotstart= 0
Write HDF5 File= 1
Write Binary Output= 1
Write DSS Sediment File= 0
DSS Sediment Output Type= 1
SV Curve= 0
Specific Gage Flag= 0
Subcell Erosion Methods= 0
Subcell Deposition Methods= 0
Advection Scheme= 1
Matrix Solver= 0
Implicit Weighting Factor= 1
Maximum Outer Loop Convergence Iterations= 5
Convergence Maximum Absolute= 0.001
Convergence RMSE= 0.0001
Grain Fractions Max Abs Error= 0.001
Max Subgrid Regions= 1
Max Subgrid Length Scale= 3.402823E+38
Initial Layer Thickness= 3
Min Layer Thickness= 0.1
Max Layer Thickness= 6
Number of Layers= 5

--- DryRn.f01 (steady flow) ---

Flow Title=Flow
Program Version=6.60
Number of Profiles= 1
Profile Names=P100yr
River Rch & RM=DryRn,Main            ,2676
     752
River Rch & RM=DryRn,Main            ,1302
     841
Boundary for River Rch & Prof#=DryRn,Main            , 1
Up Type= 0
Dn Type= 3
Dn Slope=0.035081
DSS Import GetInterval= 0
DSS Import GetPeak= 0
DSS Import FillOption= 0

--- DryRn.g01 (geometry) ---

Geom Title=Geometry
Program Version=6.60

River Reach=DryRn           ,Main
Reach XY= 30
     1601203.769      449338.027     1601187.271      449288.533
     1601230.403      449141.221     1601222.176      449098.509
     1601197.603      449068.815      1601084.07      448995.823
     1601056.515      448944.917     1600999.716      448869.896
     1600942.898      448844.171     1600841.729       448819.64
      1600816.82      448809.0011600797.63557791448788.035458915
     1600803.754      448691.785     1600701.223      448549.374
1600687.05888129       448470.42     1600647.039      448386.822
     1600606.014      448320.253     1600415.838       448135.06
     1600361.412      448070.959     1600371.088      447959.688
     1600327.547      447867.7691600291.54311071447837.927166971
1600224.81849726447818.410112531     1600172.736      447813.343
1600121.17416515447791.6625571781600048.39011253447699.029720498
1599922.93722141447586.524221411     1599776.032      447435.991
1599727.59935476447371.1012150811599677.10071323447336.325573549

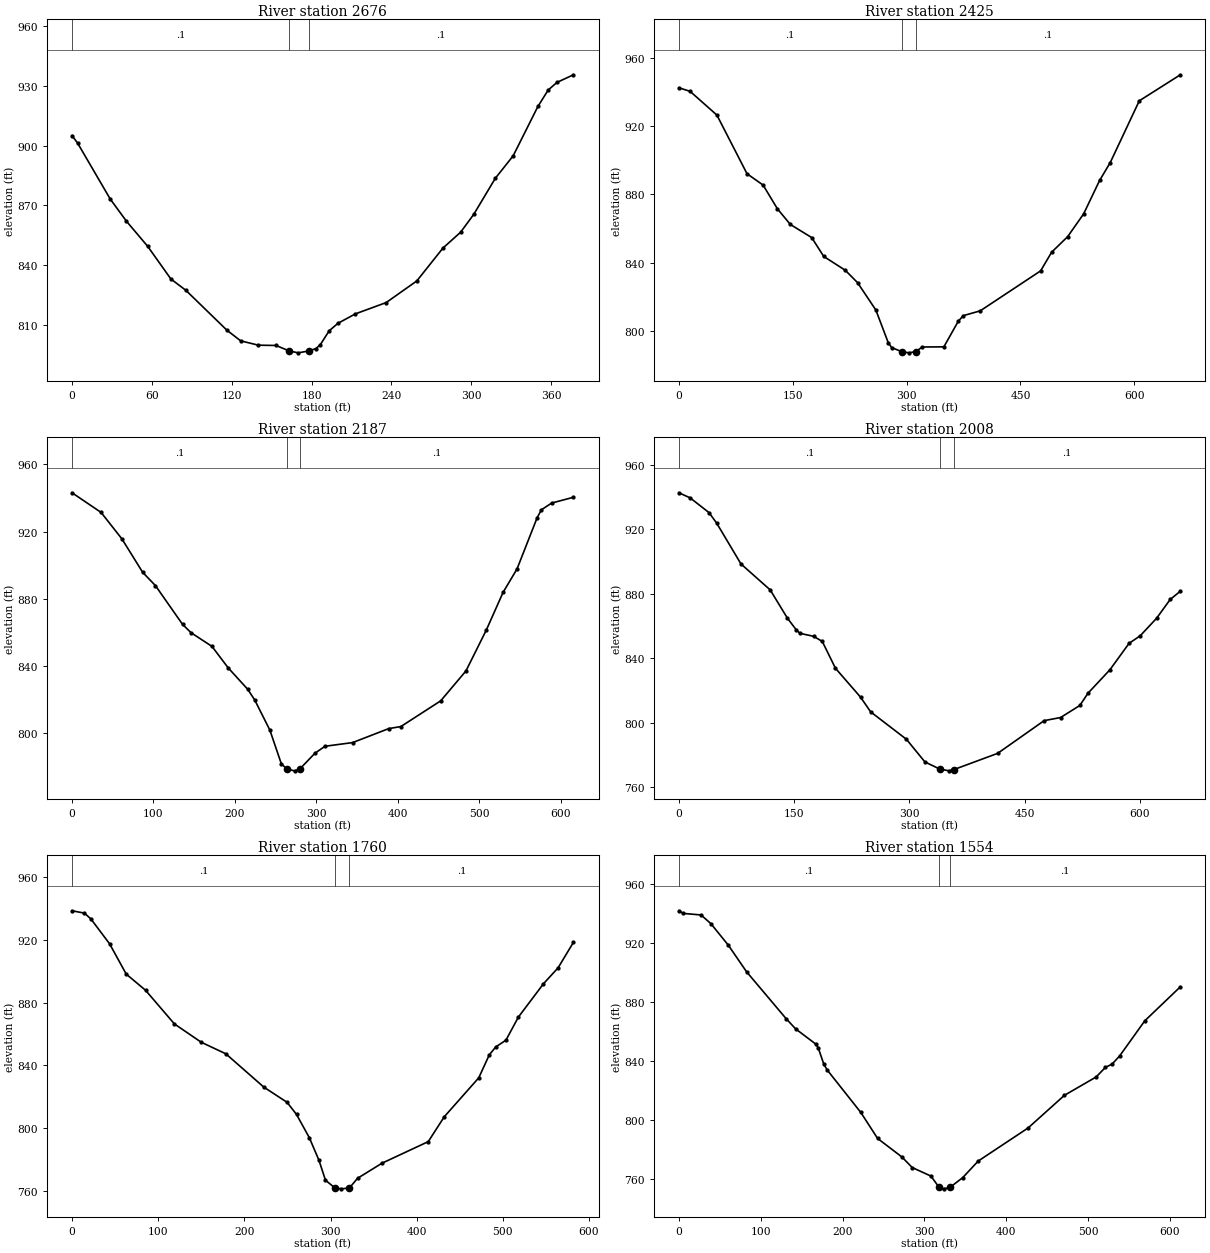
Type RM Length L Ch R = 1 ,2676    ,257.2,251.3,243.7
XS GIS Cut Line= 4
1601355.43252553449316.6045148111601242.15785534449273.743828794
1601178.88731884449262.5184110281600988.05521681449276.805306367
#Sta/Elev= 30
       0  905.03     4.2  901.24    28.7  873.21    40.9  862.09    56.8  849.54
    74.3  833.12    85.5  827.48   116.4  807.44   126.7  802.14     140  799.97
   153.3  799.82   163.2797.0675     170  796.13   177.7  797.07   183.3  798.28
   186.6   800.3   193.2  807.19   199.8  810.95   212.9  815.67     236  821.33
     259  832.16   278.7  848.68   291.9  856.58   301.8  865.55     318  883.63
   331.4  894.88     350  919.64   357.7  927.86   364.3  931.69   376.7  935.52
#Mann= 3 ,-1,0
       0      .1       0   163.2    .045       0   177.7      .1       0
Bank Sta=163.2,177.7
XS Rating Curve= 0 ,0
Exp/Cntr(USF)=0,0
Exp/Cntr=0.3,0.1

Type RM Length L Ch R = 1 ,2425    ,239.8,237.9,235.7
XS GIS Cut Line= 6
1601411.09834385 448868.712653311601338.60369544448922.766350985
1601203.91485644449018.0302680591601121.99387107449078.218382421
1600940.62284275449148.8448815971600838.31628882449186.313310597
#Sta/Elev= 30
       0   942.3    14.7  940.22      50  926.35    89.7  892.05   110.9  885.43
   129.7  871.58   146.8   862.4   174.9  854.75   190.8  843.71   219.2  835.61
   235.3  828.41   259.5  812.36   275.8  793.27   280.3  790.42   293.3788.0987
     303  787.35   312.1  788.09   320.6  790.77   349.1  790.85   368.1  805.85
   374.8  809.11     397   811.9   476.6  835.27   491.1  846.18   512.2  855.27
   533.3  868.62   554.3  888.12   568.3  898.56   606.6  934.69   660.7  949.91
#Mann= 3 ,-1,0
       0      .1       0   293.3    .045       0   312.1      .1       0
Bank Sta=293.3,312.1
XS Rating Curve= 0 ,0
Exp/Cntr(USF)=0,0
Exp/Cntr=0.3,0.1

Type RM Length L Ch R = 1 ,2187    ,181,179.3,179.7
XS GIS Cut Line= 2
1601180.52642814448667.7412572241600788.42206275449142.337524619
#Sta/Elev= 30
       0  943.11    35.6  931.43    61.2  915.66    86.7  895.75   102.4  887.82
   135.7  864.73   146.2  859.74   171.8  851.63   191.6   838.9   215.7  826.08
   224.3   819.7   242.9  801.75   256.9  781.76   263.9  778.53   273.2  777.52
  279.34  778.47   298.1  787.95   310.5  792.15   344.5  794.35   388.8  802.67
   403.7  803.89   452.6   819.2   483.6     837   508.6  861.35   529.2   883.8
   546.3  897.73   571.1  928.35   576.3  932.99   588.8  936.98   615.6  940.44
#Mann= 3 ,-1,0
       0      .1       0   263.9    .045       0  279.34      .1       0
Bank Sta=263.9,279.34
XS Rating Curve= 0 ,0
Exp/Cntr(USF)=0,0
Exp/Cntr=0.3,0.1

Type RM Length L Ch R = 1 ,2008    ,243.3,247.8,252.5
XS GIS Cut Line= 6
1601081.66384648448573.4942269771601007.30015005448645.408781305
1600933.51716113448713.3981466441600867.18691322448774.345859393
 1600813.7621513448862.0645159781600713.11635523449097.721853063
#Sta/Elev= 30
       0  942.64    14.6  939.47    39.1  930.36      49   923.9    80.8  898.47
   118.8   882.4   141.2  864.88   152.8  857.58   157.5  855.47   175.2  853.62
   186.6  850.45   203.8  833.77   236.4   815.9   249.6  806.75   296.2  789.73
   320.2  775.71   339.5  771.28   351.7  770.17   358.1770.9827   414.9     781
   475.5  801.31   496.9  803.24   521.9   810.7   532.6  818.34   561.1  832.85
   586.1  849.29   600.4  853.87   621.8  864.77   639.6  876.48   652.8  881.59
#Mann= 3 ,-1,0
       0      .1       0   339.5    .045       0   358.1      .1       0
Bank Sta=339.5,358.1
XS Rating Curve= 0 ,0
Exp/Cntr(USF)=0,0
Exp/Cntr=0.3,0.1

Type RM Length L Ch R = 1 ,1760    ,205.3,205.4,204.7
XS GIS Cut Line= 2
1601023.04188795448465.2611341141600510.94930146 448741.66257201
#Sta/Elev= 30
       0  938.68    14.4  937.18    21.9  933.45    43.5  917.65    62.9  898.26
    85.3  887.95   118.8  866.46     150  854.76   178.5   847.4   222.6  826.12
   249.5  816.45   260.5  808.72   275.4  793.82   286.6  779.38   294.1  766.73
   305.2  761.75   312.7  761.22   321.9  761.79   331.3  767.93   359.7  777.58
   413.4  791.35     432  807.24     472  832.07   484.2   846.7   491.7  851.77
   503.5  856.07     518  870.84   547.1  892.09   564.1   902.3   581.9  918.56
#Mann= 3 ,-1,0
       0      .1       0   305.2    .045       0   321.9      .1       0
Bank Sta=305.2,321.9
XS Rating Curve= 0 ,0
Exp/Cntr(USF)=0,0
Exp/Cntr=0.3,0.1

Type RM Length L Ch R = 1 ,1554    ,252.8,252.1,250.7
XS GIS Cut Line= 6
1600941.43720143448261.3575473081600723.28671909448395.798879469
1600638.03623343448448.071084643 1600573.2122161448485.837741385
1600497.31866709448529.4672473021600414.31555226448573.474049057
#Sta/Elev= 30
       0  941.77     5.3  939.99      27  938.94      39  933.08    60.2  918.59
    82.7  900.44     131  868.74   142.6  861.83   167.5  851.43   170.3   848.9
     177  838.02   181.1  834.08   222.3  805.24   242.8  787.65   272.4  775.16
   285.1  767.98     308  762.18     318754.5129   323.6  753.55   331.1 754.483
   346.7  761.07   365.8  772.38   426.6   794.7   471.1  816.84   509.9  829.28
   521.2  835.77   529.4  837.98   538.6  843.51   569.4  867.32   612.8  890.31
#Mann= 3 ,-1,0
       0      .1       0     318    .045       0   331.1      .1       0
Bank Sta=318,331.1
XS Rating Curve= 0 ,0
Exp/Cntr(USF)=0,0
Exp/Cntr=0.3,0.1

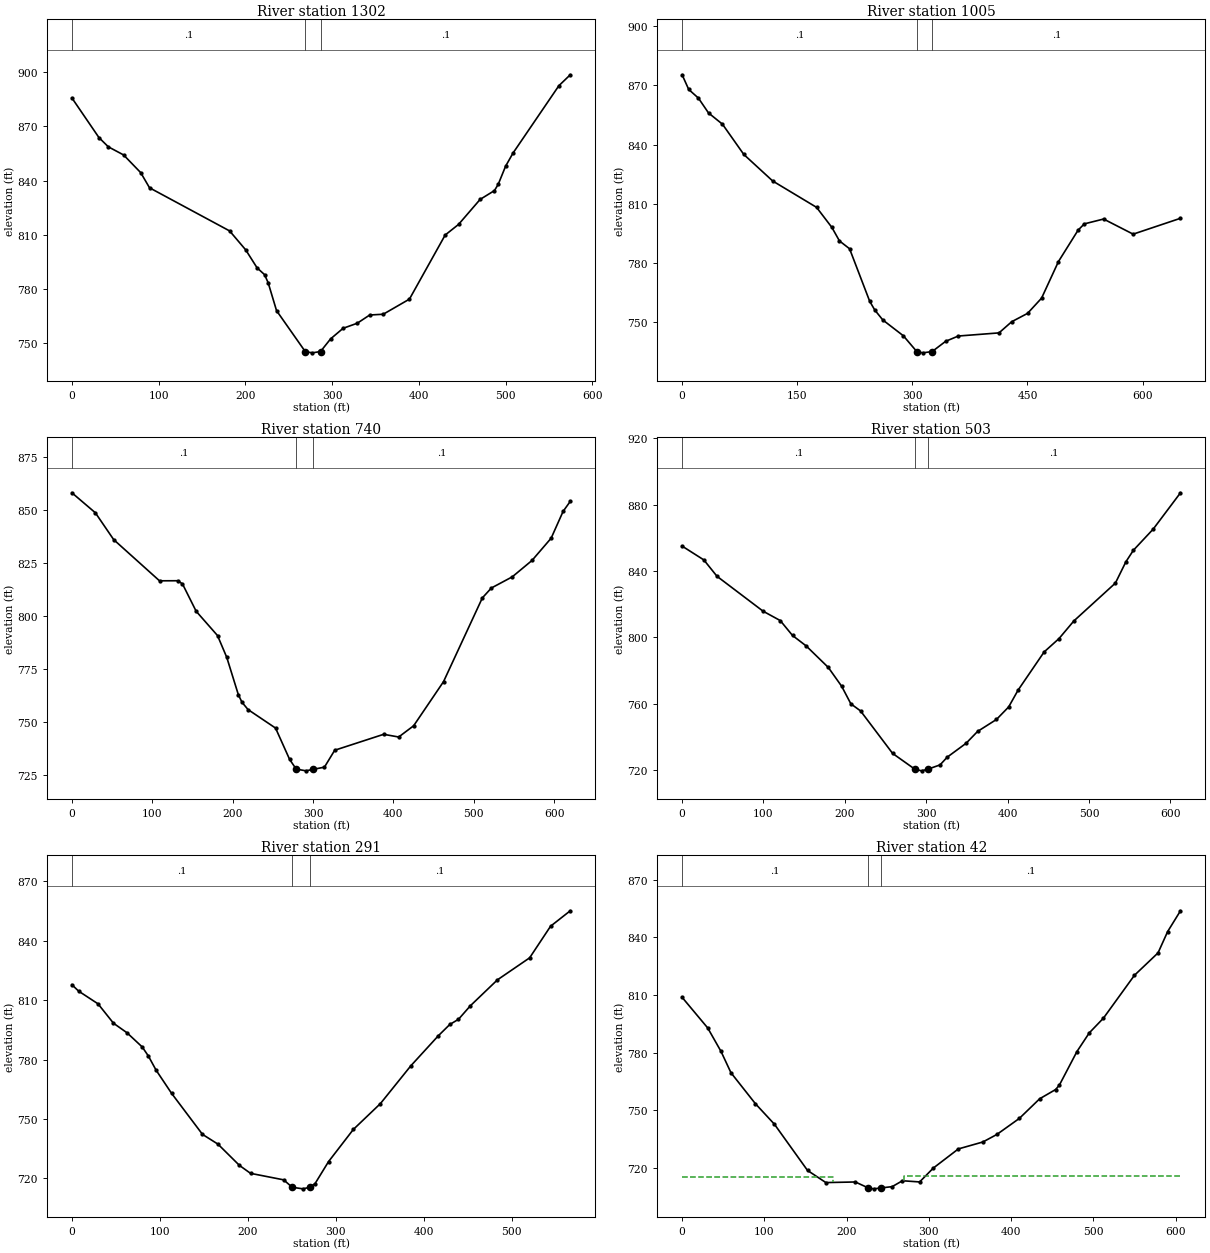
Type RM Length L Ch R = 1 ,1302    ,290.3,297.5,306.1
XS GIS Cut Line= 2
1600728.00712634448055.1273333061600287.13329807448423.429337993
#Sta/Elev= 30
       0  885.67    31.2  863.74      42  858.64    59.6  854.15    79.3  844.38
    89.5  835.99   181.8  812.15   200.4  801.65   213.5  791.71   222.1  787.98
   226.3  783.43   235.9  768.08   269.1  745.38   277.3  744.75   286.6  745.48
   298.2  752.46   312.6  758.31   328.9  761.11   343.3  765.66   358.9  766.09
   389.1  774.45   430.3  809.88   445.7  815.74   470.6  829.58   487.1  834.45
   491.5  837.97   499.9  847.87   508.5  855.19   561.4  892.45   574.5  898.47
#Mann= 3 ,-1,0
       0      .1       0   269.1    .045       0   286.6      .1       0
Bank Sta=269.1,286.6
XS Rating Curve= 0 ,0
Exp/Cntr(USF)=0,0
Exp/Cntr=0.3,0.1

Type RM Length L Ch R = 1 ,1005    ,273.2,264.5,250.7
XS GIS Cut Line= 6
1600676.24897489447953.1345753071600583.29870147447985.189629316
1600495.50983505448005.1945105641600320.97671956447991.829707891
1600243.79085031448002.4861826451600062.09337905448103.078173056
#Sta/Elev= 30
       0  875.41     8.6  867.96    21.2  863.59    34.4  856.05    52.6  850.33
    80.4  834.99     118  821.54   175.2  808.16   195.2  797.95     205  791.14
   218.2  787.16   244.4  760.54     251  756.11   261.5  751.05   288.3  743.01
   305.8735.0073   313.7  734.37   325.8735.0233   343.4  740.22   359.9   742.9
   412.9  744.49   429.5  750.16   450.1  754.38   468.4  762.12   490.4  780.69
     516  796.62   524.1  799.79   549.2  802.24   587.7  794.57   649.4  802.62
#Mann= 3 ,-1,0
       0      .1       0   305.8    .045       0   325.8      .1       0
Bank Sta=305.8,325.8
XS Rating Curve= 0 ,0
Exp/Cntr(USF)=0,0
Exp/Cntr=0.3,0.1

Type RM Length L Ch R = 1 ,740     ,234.2,237.1,238.6
XS GIS Cut Line= 3
1600363.03743836447567.6656600261600158.29563251447917.631304908
1599969.02849804448018.811848496
#Sta/Elev= 30
       0  858.17    29.2  848.74      52  836.08     109  816.67   131.8   816.7
   137.6   815.2   154.6  802.32   181.2  790.85   192.7  780.57   207.1  762.98
   211.6  759.42   219.2  755.95   253.4  747.24   270.9  732.46   279.1   727.9
   291.4  727.08   299.5727.7459   314.2  728.81     327  736.79   387.9   744.3
   406.6  743.03   425.2  748.32   462.4  769.13   510.7  808.61   521.9  813.27
   547.9  818.53   572.5  826.27   596.3  836.76   611.2  849.41   620.1  854.12
#Mann= 3 ,-1,0
       0      .1       0   279.1    .045       0   299.5      .1       0
Bank Sta=279.1,299.5
XS Rating Curve= 0 ,0
Exp/Cntr(USF)=0,0
Exp/Cntr=0.3,0.1

Type RM Length L Ch R = 1 ,503     ,213.1,212.4,211.9
XS GIS Cut Line= 6
1600247.17371756447480.903892472 1600117.0135448447607.038482726
1599991.34155205447728.8233441411599937.48240781447781.016809314
1599874.64624739447841.9094040541599807.32190697447907.151071474
#Sta/Elev= 30
       0     855    26.7  846.68    42.9  836.81    99.5  815.82   120.6  810.17
   135.7  801.19   152.5  794.89   179.7  781.93   196.1   770.6   207.4  760.04
   219.3  755.78   258.7   730.2   285.9 720.742   294.2  719.71   302.3  720.75
     317  723.29   325.8  727.94     349   736.3   363.1  743.42   386.3  750.63
   401.3  758.17   412.9   768.3   444.9  791.28   463.2  799.33   481.4  809.92
   532.5  832.74   545.4  845.56   554.6  852.49   578.9   865.2   612.5   887.1
#Mann= 3 ,-1,0
       0      .1       0   285.9    .045       0   302.3      .1       0
Bank Sta=285.9,302.3
XS Rating Curve= 0 ,0
Exp/Cntr(USF)=0,0
Exp/Cntr=0.3,0.1

Type RM Length L Ch R = 1 ,291     ,248.4,248.7,249.2
XS GIS Cut Line= 2
1600053.08916701447347.5520533651599675.71568438 447770.28292574
#Sta/Elev= 30
       0  817.83     7.7  814.58    29.7  808.18    47.3  798.38    62.7  793.55
      80  786.38    86.9  781.87    95.7  774.71   113.3  763.01   148.5  742.25
   166.1  737.32   190.5  726.59   203.1  722.58   240.8  719.29   250.5715.5377
   262.8  714.75  270.42  715.55   276.5   717.4   291.8  728.48     320  744.73
   350.8  757.79   385.4  776.88   416.7  792.07   429.7  797.75   439.6  800.37
   453.1   807.2   483.9   820.3   520.5  831.41   544.3  847.37   566.7  855.17
#Mann= 3 ,-1,0
       0      .1       0   250.5    .045       0  270.42      .1       0
Bank Sta=250.5,270.42
XS Rating Curve= 0 ,0
Exp/Cntr(USF)=0,0
Exp/Cntr=0.3,0.1

Type RM Length L Ch R = 1 ,42      ,,,
XS GIS Cut Line= 3
1599872.93248267447185.7922810391599637.28396738447439.781758443
1599567.78761327   447689.797091
#Sta/Elev= 30
       0  808.77    31.1  792.85    47.3  780.63    59.4  769.53    89.1  753.43
   112.2  742.77   152.5   718.7   174.8  712.39   210.6   712.7   226.1  709.66
     233  709.13     242  709.61   255.4  710.27   267.9  713.34   288.8  712.72
   305.4  719.92   335.9   729.9   365.7  733.51   382.7  737.42     410  745.76
   434.8     756   454.2  760.81   458.8  763.17   480.1  780.58   495.1  790.29
   512.3  797.94     550  820.24   578.7   831.9   590.4  843.01     606  853.81
#Mann= 3 ,-1,0
       0      .1       0   226.1    .045       0     242      .1       0
#XS Ineff= 2 , 0
          183.74  715.38  270.02          715.87
Permanent Ineff=
       F       F
Bank Sta=226.1,242
XS Rating Curve= 0 ,0
Exp/Cntr(USF)=0,0
Exp/Cntr=0.3,0.1
LCMann Table=0

Chan Stop Cuts=-1
Use User Specified Reach Order=0
Composite Channel Slope=5